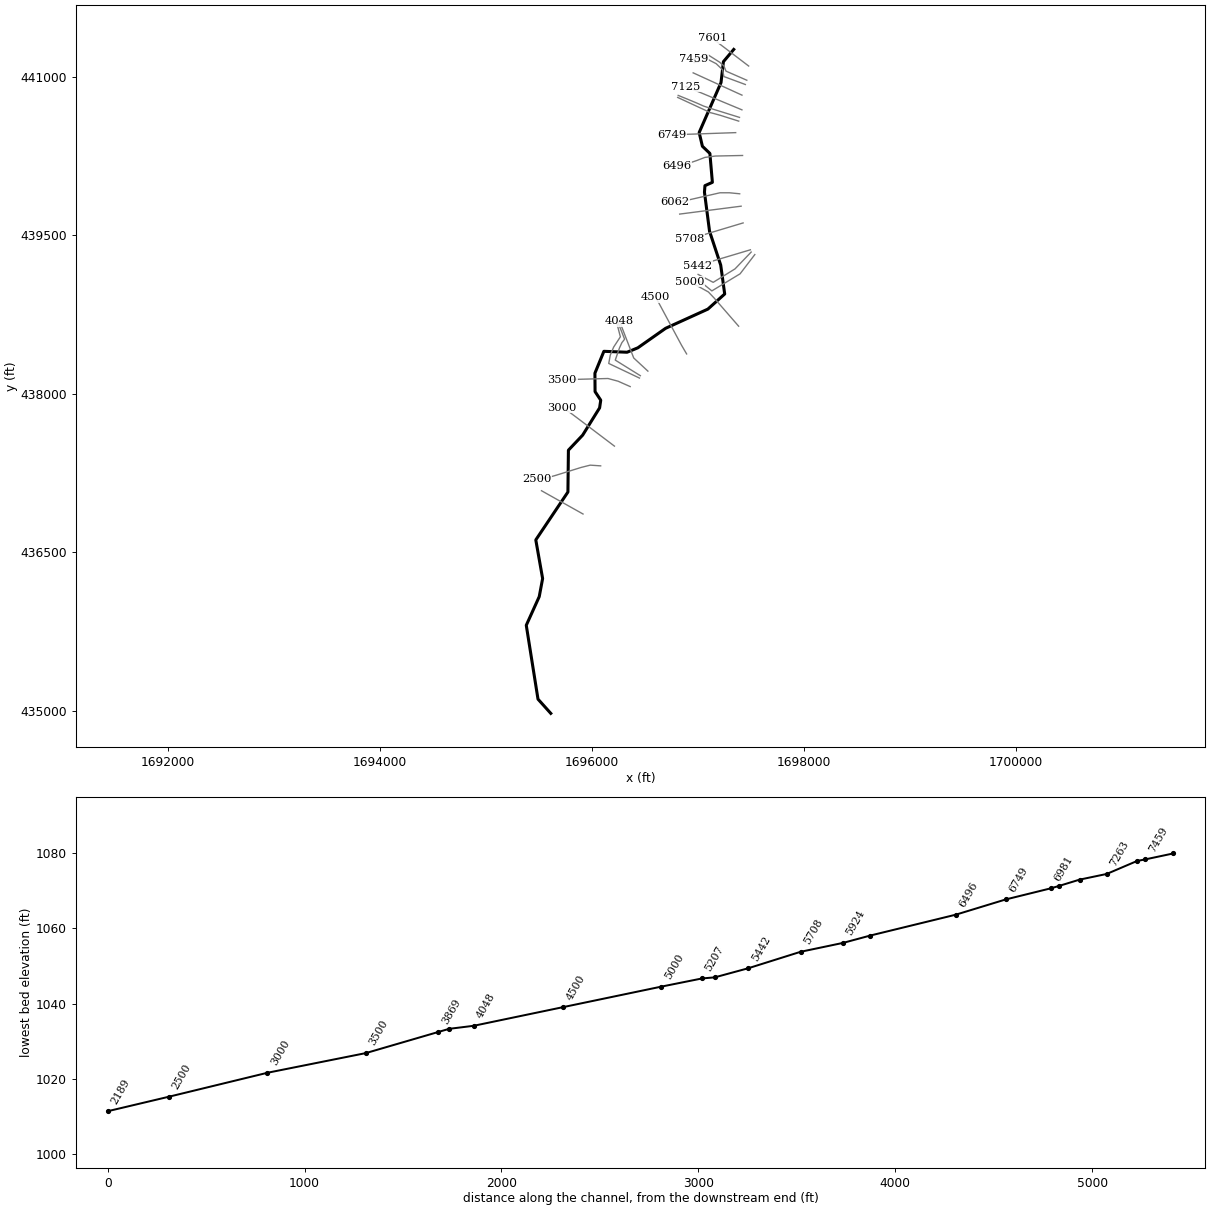
--- RCKCMPRN1.prj (project) ---

Proj Title=RCKCMPRN1
Current Plan=p01
Default Exp/Contr=0,0
English Units
Geom File=g01
Flow File=f01
Plan File=p01
BEGIN DESCRIPTION:
---------- MODELED AS PART OF WVEMD CTP PROGRAM, 2023----------
Stream Name: Rockcamp Run
Flood Zone:  AFH
Wetzel County, WV
HEC-RAS Version: RAS 6.3
Vertical Datum: NAVD88
Projection: NAD 1983 StatePlane West Virginia S FIPS 4702 (US Feet)
Terrain: 1-meter West Virginia FEMA R3 South Central (collected 2018-2020)
Land Use: 2019 NLCD
Hydrologic Method:
WV SIR2010-5033 regression equations
Additional Model Notes:
None
END DESCRIPTION:
DSS Export Rating Curves= 0
DSS Export Rating Curve Sorted= 0
DSS Export Volume Flow Curves= 0
DXF OffsetX= 0
DXF OffsetY= 0
DXF ScaleX= 0
DXF ScaleY= 0

--- RCKCMPRN1.p01 (plan) ---

Plan Title=Floodplain
Program Version=6.30
Geom File=g01
Flow File=f01
Subcritical Flow
K Sum by GR= 0
Std Step Tol= 0.01
Critical Tol= 0.01
Num of Std Step Trials= 20
Max Error Tol= 0.3
Flow Tol Ratio= 0.001
Split Flow NTrial= 30
Split Flow Tol= 0.02
Split Flow Ratio= 0.02
Log Output Level= 0
Friction Slope Method= 1
Unsteady Friction Slope Method= 2
Unsteady Bridges Friction Slope Method= 1
Parabolic Critical Depth
Global Vel Dist= 0 , 0 , 0
Global Log Level= 0
CheckData=True
Encroach Param=-1 ,0,0, 0
Mapping Interval=1HOUR
Computation Time Step Use Courant=        0
Computation Time Step Use Time Series=    0
Computation Time Step Count To Double=0
Computation Time Step Max Doubling=0
Computation Time Step Max Halving=0
Computation Time Step Residence Courant=0
Run HTab= 0
Run UNet= 0
Run Sediment= 0
Run PostProcess= 0
Run WQNet= 0
Run RASMapper= 0
UNET Theta= 0
UNET Theta Warmup= 0
UNET ZTol= 0
UNET ZSATol= 0
UNET MxIter= 0
UNET Max Iter WO Improvement= 0
UNET MaxInSteps= 0
UNET DtIC= 0
UNET DtMin= 0
UNET MaxCRTS= 0
UNET WFStab= 0
UNET SFStab= 0
UNET WFX= 1
UNET SFX= 1
UNET Gravity=32.17405
UNET 1D Methodology=Finite Difference
UNET DSS MLevel= 1
UNET Pardiso=0
UNET DZMax Abort= 0
UNET Use Existing IB Tables= 0
UNET Froude Reduction=False
UNET Froude Limit= 0
UNET Froude Power= 0
UNET D1 Cores= 0
UNET WindReference=Eulerian
UNET WindDragFormulation=Hsu (1988)
UNET D2 Coriolis=0
UNET D2 Cores= 0
UNET D2 Theta= 1
UNET D2 Theta Warmup= 1
UNET D2 Z Tol= 0.01
UNET D2 Volume Tol= 0.01
UNET D2 Max Iterations= 20
UNET D2 Equation= 0
UNET D2 RampUpFraction=0.1
UNET D2 TimeSlices= 1
UNET D2 Turbulence Formulation=Non-Conservative (original)
UNET D2 Eddy Viscosity=0.3
UNET D2 Transverse Eddy Viscosity=0.1
UNET D2 Smagorinsky Mixing=0
UNET D2 BCVolumeCheck=0
UNET D2 Cores=0
UNET D2 SolverType=PARDISO (Direct)
UNET D2 Minimum Iterations= 3
UNET D2 Maximum Iterations= 30
UNET D2 Restart Number= 10
UNET D2 Relaxation Coeff=1.3
UNET D2 SOR Precondition Iterations= 10
UNET D2 ILUT Maximum Fill= 8
UNET D2 ILUT Tolerance=1E-08
UNET D2 Convergence Tolerance=0.00001
UNET D1D2 MaxIter= 0
UNET D1D2 ZTol=0.01
UNET D1D2 QTol=0.1
UNET D1D2 MinQTol=1
Write IC File= 0
Write IC File at Fixed DateTime=0
Write IC File at Sim End=0
Echo Input=False
Echo Parameters=False
Echo Output=False
Write Detailed= 0
HDF Write Warmup=0
HDF Write Time Slices=0
HDF Flush=0
HDF Compression= 1
HDF Chunk Size= 1
HDF Spatial Parts= 1
HDF Use Max Rows=0
HDF Fixed Rows= 1
Calibration Method= 0
Calibration Iterations= 20
Calibration Max Change=0.05
Calibration Tolerance=0.2
Calibration Maximum=1.5
Calibration Minimum=0.5
Calibration Optimization Method= 1
WQ AD Non Conservative
WQ ULTIMATE=-1
WQ Max Comp Step=1HOUR
WQ Output Interval=15MIN
WQ Output Selected Increments= 0
WQ Output face flow=0
WQ Output face velocity=0
WQ Output face area=0
WQ Output face dispersion=0
WQ Output cell volume=0
WQ Output cell surface area=0
WQ Output cell continuity=0
WQ Output cumulative cell continuity=0
WQ Output face conc=0
WQ Output face dconc_dx=0
WQ Output face courant=0
WQ Output face peclet=0
WQ Output face adv mass=0
WQ Output face disp mass=0
WQ Output cell mass=0
WQ Output cell source sink temp=0
WQ Output nsm pathways=0
WQ Output nsm derived pathways=0
WQ Create Restart=0
WQ Fixed Restart=0
WQ System Summary=0
WQ Write To DSS=0
Sorting and Armoring Iterations= 10
XS Update Threshold= 0.02
Bed Roughness Predictor= 0
Hydraulics Update Threshold= 0.02
Energy Slope Method= 1
Volume Change Method= 1
Sediment Retention Method= 0
Sediment TS Multiplier= 1
Warm Up Method= 0
XS Weighting Method= 0
Number of US Weighted Cross Sections= 1
Number of DS Weighted Cross Sections= 1
Upstream XS Weight=0
Main XS Weight=1
Downstream XS Weight=0
Number of DS XS's Weighted with US Boundary= 1
Upstream Boundary Weight= 1
Weight of XSs Associated with US Boundary= 0
Number of US XS's Weighted with DS Boundary= 1
Downstream Boundary Weight= 0.5
Weight of XSs Associated with DS Boundary= 0.5
Percentile Method= 0
Sediment Output Level= 3
Mass or Volume Output= 0
Output Increment Type= 1
Profile and TS Output Increment= 1
Transport Output Increment 1
XS Output Flag= 0
XS Output Increment= 10
Read HDF5 Sediment Hotstart= 0
Sediment Hotstart Type= 0
Write Gradation File= 0
Read Gradation Hotstart= 0
Write HDF5 File= 1
Write Binary Output= 1
Write DSS Sediment File= 0
DSS Sediment Output Type= 1
SV Curve= 0
Specific Gage Flag= 0
Subcell Erosion Methods= 0
Subcell Deposition Methods= 0
Advection Scheme= 1
Matrix Solver= 0
Implicit Weighting Factor= 1
Maximum Outer Loop Convergence Iterations= 5
Convergence Maximum Absolute= 0.001
Convergence RMSE= 0.0001
Grain Fractions Max Abs Error= 0.001
Max Subgrid Regions= 1
Max Subgrid Length Scale= 3.402823E+38
Initial Layer Thickness= 3.402823E+38
Min Layer Thickness= 3.402823E+38
Max Layer Thickness= 3.402823E+38
Number of Layers= 5

--- RCKCMPRN1.f01 (steady flow) ---

Flow Title=Flow
Program Version=4.00
Number of Profiles=1
Profile Names=F01pct
River Rch & RM=RCKCMPRN1,Main,7601
    1020
River Rch & RM=RCKCMPRN1,Main,3869
    1160
Boundary for River Rch & Prof#=RCKCMPRN1,Main      ,1
Up Type=0
Dn Type=3
Dn Slope=0.012588

--- RCKCMPRN1.g01 (geometry) ---

Geom Title=Geometry
Program Version=6.31

River Reach=RCKCMPRN1       ,Main
Reach XY= 30
     1697336.929      441259.009     1697239.716      441143.428
     1697216.932      440945.033     1697010.857      440472.725
     1697041.321       440342.68     1697111.975      440274.586
     1697135.526      440001.185     1697065.384      439969.698
1697060.79498055439907.906188218     1697108.647      439538.605
     1697214.116      439217.846     1697251.696      438944.428
     1697093.049      438801.344     1696694.108      438619.487
     1696432.244      438434.898     1696330.393       438393.12
     1696111.945      438401.858     1696027.297      438194.879
     1696028.662      438020.394     1696082.182      437939.295
     1696071.533      437866.661     1695911.519      437608.347
     1695777.174      437466.083     1695772.532      437070.146
     1695469.436      436616.868     1695533.878      436251.241
      1695501.93      436080.032       1695379.6      435808.884
     1695490.189      435109.852      1695610.83      434975.071

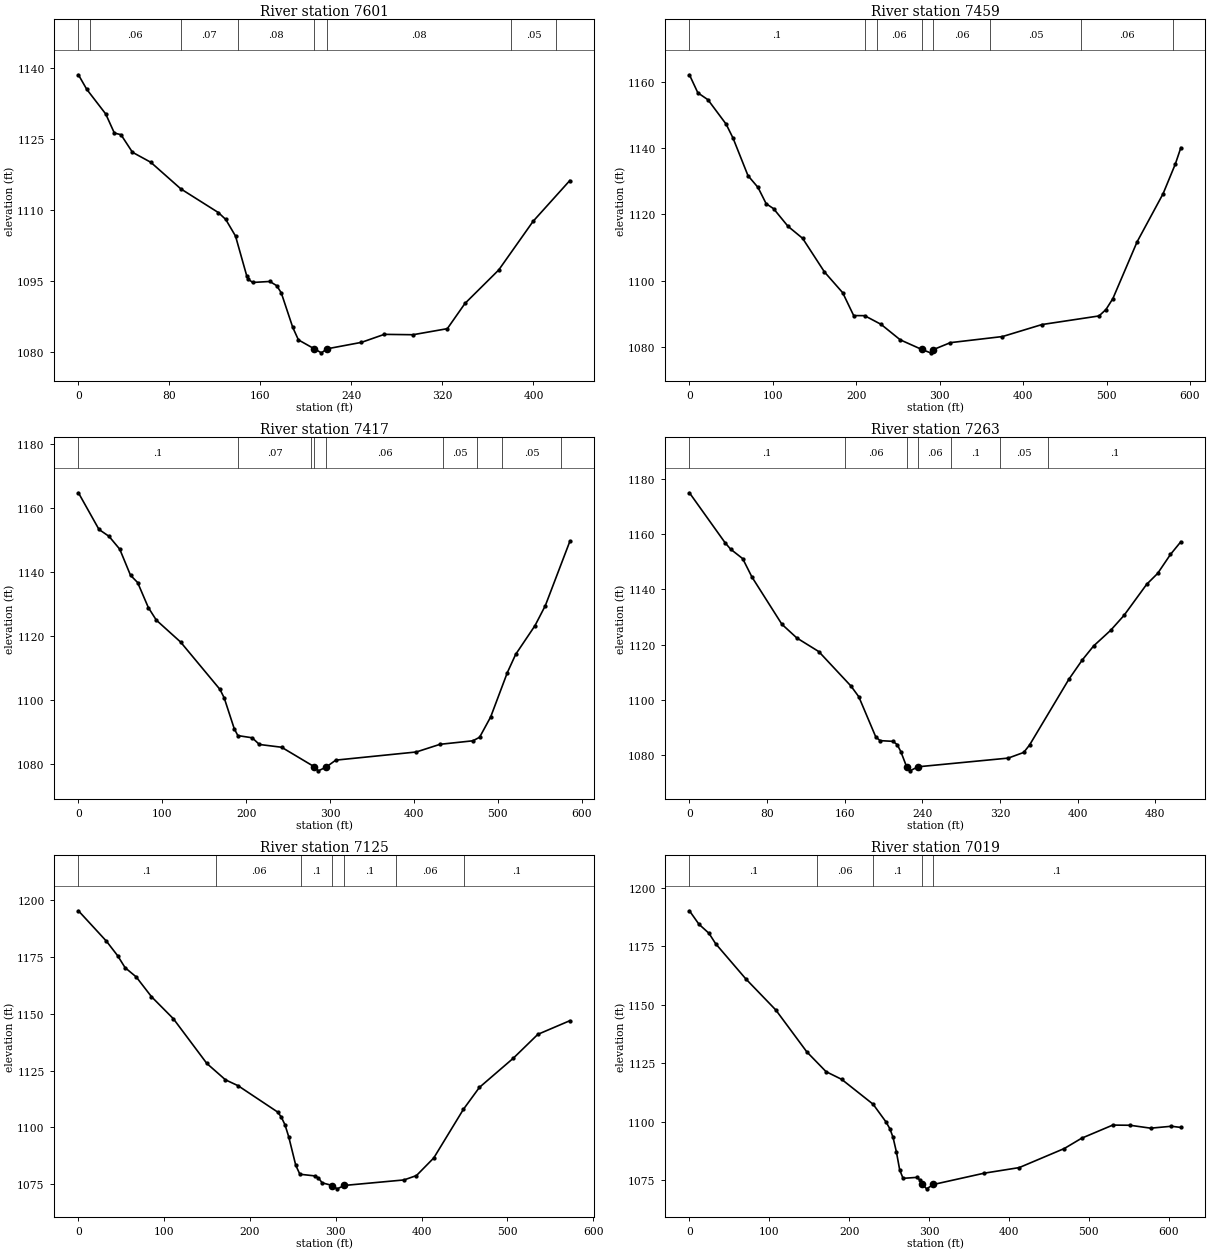
Type RM Length L Ch R = 1 ,7601    ,143.7,143,141.6
BEGIN DESCRIPTION:
Structure XS 4
END DESCRIPTION:
XS GIS Cut Line= 2
1697477.87773112441101.9604634151697134.44142376441364.074279208
#Sta/Elev= 30
       0 1138.56     7.3  1135.5      24 1130.29    31.6 1126.26    37.4 1125.92
    47.5 1122.21    63.6  1120.1      90 1114.49     123 1109.49   129.5 1108.04
   138.1 1104.53   148.1 1096.01   149.3 1095.43   153.2 1094.74   168.3 1094.95
   174.3 1094.06   178.3 1092.56   188.4 1085.27   193.4 1082.62  207.35 1080.74
   213.6 1079.89   218.6 1080.74   248.8  1082.1   268.9 1083.79   294.1 1083.71
   324.3 1084.99   339.8 1090.31   369.5 1097.38   399.7 1107.64     432 1116.25
#Mann= 8 ,-1,0
       0      .1       0      10     .06       0      90     .07       0
     140     .08       0  207.35    .045       0   218.6     .08       0
     380     .05       0     420      .1       0
Bank Sta=207.35,218.6
XS Rating Curve= 0 ,0
Exp/Cntr(USF)=0,0
Exp/Cntr=0.3,0.1

Type RM Length L Ch R = 1 ,7459    ,43.3,41.7,42.8
BEGIN DESCRIPTION:
Structure XS 3
END DESCRIPTION:
XS GIS Cut Line= 6
1697460.40347673440967.5431219821697264.15415824441053.570220499
1697243.99155703441102.6325501221697205.01052801441137.581058895
1697096.13248145441206.8059897321696961.71514002441168.497047424
#Sta/Elev= 30
       0 1162.09    10.1 1156.65    22.2 1154.57      44 1147.21    52.3 1142.99
    70.2 1131.69    82.2 1128.15      92 1123.23   100.8 1121.76   118.2 1116.42
   135.7  1112.8   161.9 1102.66   183.7 1096.43   196.9 1089.53     210  1089.5
   229.7 1086.89   252.7 1082.22   278.6 1079.31   289.1  1078.3  292.381079.277
   312.8 1081.37   375.3 1083.21   422.7 1086.83     491 1089.42   499.3 1091.34
   507.6 1094.64   536.7 1111.77   567.8 1126.24   582.5  1135.2   589.1 1140.12
#Mann= 8 ,-1,0
       0      .1       0     210     .07       0  224.28     .06       0
   278.6    .045       0  292.38     .06       0  360.36     .05       0
  469.38     .06       0  579.38      .1       0
Bank Sta=278.6,292.38
XS Rating Curve= 0 ,0
Exp/Cntr(USF)=0,0
Exp/Cntr=0.3,0.1

Type RM Length L Ch R = 1 ,7417    ,150.2,154.2,155.2
BEGIN DESCRIPTION:
Structure XS 2
END DESCRIPTION:
XS GIS Cut Line= 6
1697446.28965588440927.2179195531697243.99155703441002.491630755
 1697231.8939963441066.3398679351697171.40619265441124.139324751
1697090.75578779441165.8087005951696963.73140014441134.892712066
#Sta/Elev= 30
       0 1164.88    24.5 1153.41    36.5 1151.25    49.3 1147.22    62.1 1139.07
    70.6  1136.8    83.4 1128.95    92.9 1125.03   121.8 1118.19   168.8 1103.35
   173.8 1100.72   185.8 1091.07   190.1 1088.91   207.2 1088.22   215.8 1086.13
   242.3 1085.26  281.391079.138   286.1 1077.88   295.5 1079.07   306.9 1081.23
   402.9 1083.78   431.2 1086.18   470.4 1087.28   478.4 1088.39   491.6 1094.75
   511.5 1108.64   521.4 1114.32   544.5 1123.34   556.8 1129.59     586 1149.68
#Mann= 9 ,-1,0
       0      .1       0     190     .07       0  277.89     .06       0
  281.39    .045       0   295.5     .06       0  434.51     .05       0
  475.29     .06       0  505.29     .05       0  575.29      .1       0
Bank Sta=281.39,295.5
XS Rating Curve= 0 ,0
Exp/Cntr(USF)=0,0
Exp/Cntr=0.3,0.1

Type RM Length L Ch R = 1 ,7263    ,137.9,137.9,138.7
BEGIN DESCRIPTION:
Structure XS 1
END DESCRIPTION:
XS GIS Cut Line= 2
1697414.70158065440826.4049134781696954.32218624441037.440139527
#Sta/Elev= 30
       0 1174.85    36.7 1156.83    42.4  1154.5    54.9 1151.06    64.4 1144.44
    95.3 1127.36   110.7 1122.41   133.3  1117.5   166.5 1105.04   174.5 1101.21
   192.1 1086.62   196.5 1085.34   209.7 1085.08   214.1  1083.9   217.8 1081.41
   223.8 1075.92   227.3 1074.43   235.5 1075.89   328.5 1079.03   344.5 1081.08
   350.5 1083.76   390.9 1107.44   404.8 1114.46   416.5 1119.53   434.1 1125.19
   447.8 1130.55   471.2  1141.8   482.5 1145.73   495.7 1152.58   506.4 1157.17
#Mann= 7 ,-1,0
       0      .1       0     160     .06       0   223.8    .045       0
   235.5     .06       0     270      .1       0     320     .05       0
     370      .1       0
Bank Sta=223.8,235.5
XS Rating Curve= 0 ,0
Exp/Cntr(USF)=0,0
Exp/Cntr=0.3,0.1

Type RM Length L Ch R = 1 ,7125    ,104.9,105.4,105.8
BEGIN DESCRIPTION:
Structure XS 4
END DESCRIPTION:
XS GIS Cut Line= 2
1697414.29233875 440687.339039531696885.75007645440908.048995215
#Sta/Elev= 30
       0 1195.33    32.7 1181.92    45.7 1175.56    54.4 1170.28    67.4  1166.2
    85.1 1157.53   110.7 1147.79   149.7 1128.11   171.4 1120.91   186.1 1118.32
   232.1 1106.76   236.4 1104.57   240.8 1101.08   245.1 1095.87   253.3 1083.32
   258.1 1079.35   275.4 1078.62   279.8 1077.69   284.1 1075.56   296.1 1074.38
   301.5 1072.92   310.1 1074.42   379.5 1076.84     394 1078.76   414.2 1086.52
   448.8 1107.96   467.4 1117.58   507.1 1130.49   535.5 1140.93   572.8 1146.94
#Mann= 7 ,-1,0
       0      .1       0     160     .06       0     260      .1       0
   296.1    .045       0   310.1      .1       0     370     .06       0
     450      .1       0
Bank Sta=296.1,310.1
XS Rating Curve= 0 ,0
Exp/Cntr(USF)=0,0
Exp/Cntr=0.3,0.1

Type RM Length L Ch R = 1 ,7019    ,39.6,38.6,37.1
BEGIN DESCRIPTION:
Structure XS 3
END DESCRIPTION:
XS GIS Cut Line= 6
1697391.47072918440615.8686530181697151.95170452440690.433063913
1697054.12774108440722.4017094111696984.73417909440753.152632166
1696901.86131334440787.7824841621696813.11936484440823.900522161
#Sta/Elev= 30
       0 1190.27    11.9 1184.52    24.5 1180.62    32.8 1176.18    70.5 1161.15
   108.2 1147.78     147 1129.86   171.1 1121.39   190.6 1118.11     230 1107.45
     246 1099.93   250.9 1097.01   254.9 1093.32   259.1 1087.11   263.3  1079.3
   267.5 1075.72   284.4 1076.13   288.6 1075.07  291.731073.206     297 1071.23
   305.4 1073.09     369 1077.93   412.9 1080.32   469.4 1088.49     491 1092.89
     530 1098.52   551.6 1098.45   577.5  1097.2   603.4 1098.02   615.3 1097.52
#Mann= 5 ,-1,0
       0      .1       0     160     .06       0     230      .1       0
  291.73    .045       0   305.4      .1       0
Bank Sta=291.73,305.4
XS Rating Curve= 0 ,0
Exp/Cntr(USF)=0,0
Exp/Cntr=0.3,0.1

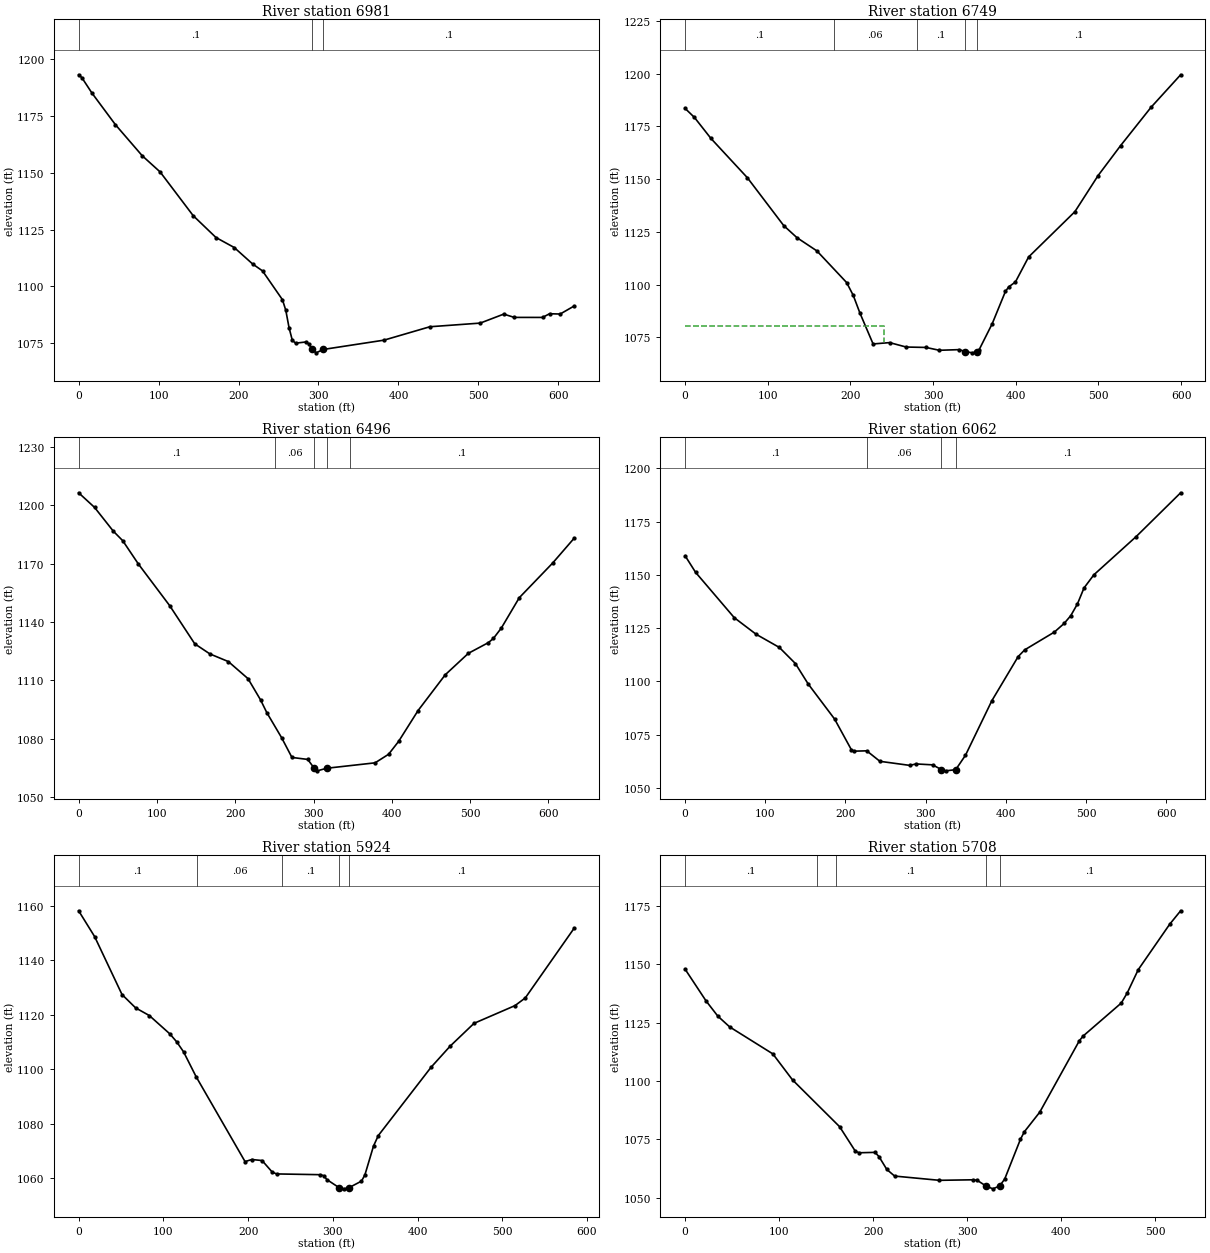
Type RM Length L Ch R = 1 ,6981    ,228.1,231.6,235.4
BEGIN DESCRIPTION:
Structure XS 2
END DESCRIPTION:
XS GIS Cut Line= 6
1697383.93942834440580.4712713791697210.18222993 440635.47936347
1697137.80606235440655.4411297811697108.10583973440662.646109256
1697076.26767939440679.9135217741696808.23380054440804.720525557
#Sta/Elev= 30
       0 1193.21       4 1191.97    16.6 1185.18      46 1171.22    79.6  1157.5
   101.9 1150.39   143.3  1131.1   171.8 1121.47   194.6 1117.07   217.6 1109.82
     230 1106.76   254.9 1094.07   259.1 1089.42   263.2 1081.69   267.3 1076.13
   271.4 1074.91   283.8 1075.41   287.9 1074.63   292.2 1072.18     297 1070.64
   306.1 1072.14   381.9 1076.23   439.3 1082.14   502.3 1083.75   531.7 1087.71
   544.9 1086.26   580.2 1086.25     589 1087.87   602.3 1087.75   619.8 1091.29
#Mann= 3 ,-1,0
       0      .1       0   292.2    .045       0   306.1      .1       0
Bank Sta=292.2,306.1
XS Rating Curve= 0 ,0
Exp/Cntr(USF)=0,0
Exp/Cntr=0.3,0.1

Type RM Length L Ch R = 1 ,6749    ,251.8,253,251.9
BEGIN DESCRIPTION:
Structure XS 1
END DESCRIPTION:
XS GIS Cut Line= 2
1697355.38103479440471.6075038981696756.31115507 440450.86408701
#Sta/Elev= 30
       0  1183.5    11.3 1179.22    31.3 1169.25    75.3 1150.66   119.3 1127.96
   135.3 1122.24   159.4 1115.97   195.4 1100.96   203.4 1094.88   211.6 1086.38
   227.4 1071.86   247.4  1072.5   267.4  1070.4   291.4 1070.21   307.5 1068.86
   331.5 1069.17   338.8 1068.27   347.5 1067.65  353.06 1068.28   355.5    1069
   371.5 1081.47   387.5 1096.78   391.5 1098.93   399.5  1101.2   415.5 1113.08
   471.5 1134.56   499.6 1151.69   526.7 1165.83   563.6 1184.03   599.4 1199.44
#Mann= 5 ,-1,0
       0      .1       0     180     .06       0     280      .1       0
   338.8    .045       0  353.06      .1       0
#XS Ineff= 2 , 0
          241.19 1080.33
Permanent Ineff=
       F       F
Bank Sta=338.8,353.06
XS Rating Curve= 0 ,0
Exp/Cntr(USF)=0,0
Exp/Cntr=0.3,0.1

Type RM Length L Ch R = 1 ,6496    ,430.8,434,431.1
XS GIS Cut Line= 6
1697420.36618184440255.3766769171697164.17181234440250.041713834
1697064.46105376440237.0131965881696990.74040067440208.489631593
1696901.98434459 440178.140282841696801.32345667440155.785668761
#Sta/Elev= 30
       0  1206.3    20.3 1198.81    44.3 1186.59    56.3 1181.72    76.3 1169.75
   116.3 1148.36   148.3 1128.79   167.6 1123.61   191.2 1119.68   216.3 1110.92
   232.3 1100.03   240.3 1093.48   259.2 1080.62   272.4 1070.48   292.6 1069.47
   300.7 1065.01   304.7 1063.61   316.8 1064.94   378.6 1067.72   395.8 1072.11
   408.6 1078.71   433.5 1094.57   468.2 1112.92   497.7 1123.92   523.2 1129.39
   529.7 1131.57   539.8 1136.89   562.7 1152.45   605.3 1170.23   632.8 1182.99
#Mann= 5 ,-1,0
       0      .1       0  251.25     .06       0   300.7    .045       0
   316.8     .06       0  346.25      .1       0
Bank Sta=300.7,316.8
XS Rating Curve= 0 ,0
Exp/Cntr(USF)=0,0
Exp/Cntr=0.3,0.1

Type RM Length L Ch R = 1 ,6062    ,138.9,138.3,137.7
XS GIS Cut Line= 6
1697393.13527687439892.8010409591697296.51703179439902.320378881
1697207.21406078439902.3371111271696963.54394445439846.435976219
1696878.25868195439826.8694142961696785.36943203439812.498051968
#Sta/Elev= 30
       0 1159.01    13.1 1151.22    61.3 1129.95    88.5 1122.18   117.5 1115.99
   137.5 1108.44   153.5 1098.83   186.4 1082.38   207.2 1068.07   210.1  1067.3
   226.5 1067.46   242.9 1062.54   279.9 1060.64   288.1 1061.31   308.6 1060.88
   319.7 1058.64     325 1058.07   337.4 1058.61   349.6 1065.37   382.5 1090.98
   415.3 1111.69   423.5 1114.86   460.4 1123.18   472.7 1127.27   480.9  1130.9
   489.2 1136.38   497.4 1143.89   509.7 1150.07   562.5 1168.03   617.9 1188.57
#Mann= 4 ,-1,0
       0      .1       0  226.39     .06       0   319.7    .045       0
   337.4      .1       0
Bank Sta=319.7,337.4
XS Rating Curve= 0 ,0
Exp/Cntr(USF)=0,0
Exp/Cntr=0.3,0.1

Type RM Length L Ch R = 1 ,5924    ,214.4,215.9,216.9
XS GIS Cut Line= 2
1697406.85894522439775.5355696691696826.89520223439700.657621631
#Sta/Elev= 30
       0 1158.11    18.9 1148.63    51.2 1127.39    67.3 1122.48    83.4 1119.69
   107.6 1112.97   115.7 1110.05   123.8 1106.39   138.6 1097.28   196.4 1066.11
   204.4 1066.88   216.5  1066.5   228.6 1062.22   233.7 1061.59   285.1 1061.31
   289.1 1060.94   293.2 1059.47  307.14  1056.6   313.3 1056.12   319.4  1056.6
   333.8 1058.95   337.8  1061.2     348 1071.83   353.7 1075.68   415.9 1100.71
   438.4 1108.45   466.6 1116.82     515 1123.33   527.1 1126.14   584.8 1151.73
#Mann= 5 ,-1,0
       0      .1       0     140     .06       0     240      .1       0
  307.14    .045       0   319.4      .1       0
Bank Sta=307.14,319.4
XS Rating Curve= 0 ,0
Exp/Cntr(USF)=0,0
Exp/Cntr=0.3,0.1

Type RM Length L Ch R = 1 ,5708    ,265.4,265.8,265.4
XS GIS Cut Line= 2
1697425.47379509439616.9759145711696921.00436318439465.045062268
#Sta/Elev= 30
       0 1147.88    22.3 1134.27    34.8 1127.76    47.4 1123.14    93.3 1111.58
   114.2 1100.44   164.3 1080.38   181.1 1069.82   185.2 1069.21   201.9 1069.38
   206.1  1067.6   214.5 1062.05   222.8 1059.22   270.4  1057.4   306.4 1057.63
   310.6 1057.39  319.91 1054.98   327.3 1053.75   334.4 1054.99   339.8 1057.92
   356.5 1074.92   360.7  1078.2   377.1 1086.61   419.2 1117.22   423.3 1119.26
   463.8 1133.38   470.2 1137.77   481.8 1147.66   515.2 1167.11   526.9 1172.91
#Mann= 5 ,-1,0
       0      .1       0     140     .06       0     160      .1       0
  319.91    .045       0   334.4      .1       0
Bank Sta=319.91,334.4
XS Rating Curve= 0 ,0
Exp/Cntr(USF)=0,0
Exp/Cntr=0.3,0.1

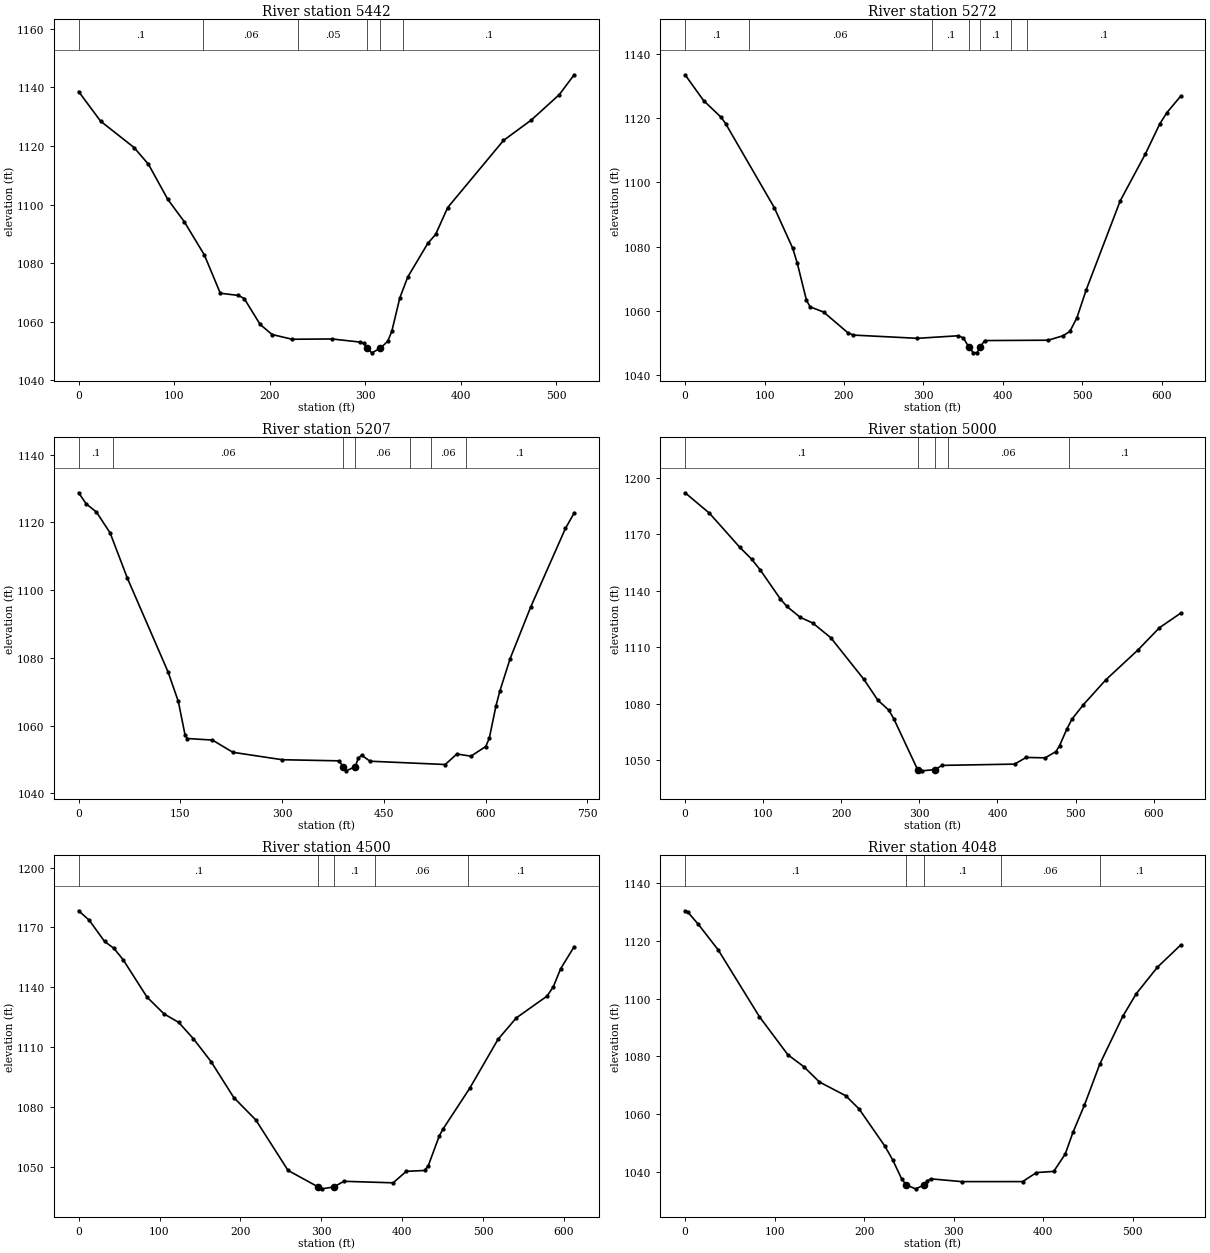
Type RM Length L Ch R = 1 ,5442    ,168.8,170.1,172.5
BEGIN DESCRIPTION:
Structure XS 4
END DESCRIPTION:
XS GIS Cut Line= 2
1697494.15471877439362.663307853 1696997.2275776439213.860578308
#Sta/Elev= 30
       0  1138.6      23 1128.49      58 1119.49    73.1 1113.76    93.3  1101.8
   110.7  1094.1   131.6 1082.81   148.3 1069.73   167.2 1068.99   173.3 1067.93
     190 1059.07   202.5 1055.64   223.4 1054.02   265.2 1054.12   294.4 1053.06
   298.6 1052.58   302.2 1050.89   306.9 1049.38  315.931050.976   323.6 1053.37
   327.8 1056.72   336.2 1068.15   344.5 1075.27   365.4 1086.72   373.7 1089.83
   386.3 1098.99   444.7  1121.9     474 1128.92   503.2 1137.58   518.7 1144.33
#Mann= 6 ,-1,0
       0      .1       0     130     .06       0     230     .05       0
   302.2    .045       0  315.93     .05       0     340      .1       0
Bank Sta=302.2,315.93
XS Rating Curve= 0 ,0
Exp/Cntr(USF)=0,0
Exp/Cntr=0.3,0.1

Type RM Length L Ch R = 1 ,5272    ,64.2,64.6,64.5
BEGIN DESCRIPTION:
Structure XS 3
END DESCRIPTION:
XS GIS Cut Line= 4
1697501.68164126439341.361839588 1697349.1648861439182.015975979
1697143.15344814439054.5392850911697000.88035563439129.659477936
#Sta/Elev= 30
       0  1133.5    23.3 1125.46    45.4 1120.26      51  1118.3   112.2 1092.18
   135.3  1079.6   141.1 1074.97   152.7 1063.36   157.3 1061.28   174.3 1059.66
   204.7 1053.25   211.5 1052.49   292.4 1051.48   344.1 1052.28   350.3 1051.56
  357.171048.764   362.9 1046.96   367.6 1047.06  371.37 1048.76     377 1050.78
     457 1050.89   475.7 1052.28   484.4 1053.66   493.2 1057.92     505 1066.67
   547.7  1094.3   579.4  1108.9   597.4  1118.2   606.5 1121.75   623.7 1126.83
#Mann= 7 ,-1,0
       0      .1       0      80     .06       0  310.57      .1       0
  357.17    .045       0  371.37      .1       0  410.57     .06       0
  430.57      .1       0
Bank Sta=357.17,371.37
XS Rating Curve= 0 ,0
Exp/Cntr(USF)=0,0
Exp/Cntr=0.3,0.1

Type RM Length L Ch R = 1 ,5207    ,218.2,207.3,191.6
BEGIN DESCRIPTION:
Structure XS 2
END DESCRIPTION:
XS GIS Cut Line= 4
1697535.82718347439317.4599600471697396.96864518439135.350401636
  1697130.633416438973.7281685461696982.66939979439093.237566253
#Sta/Elev= 30
       0 1128.73    11.2 1125.45    26.3 1123.04    46.4 1116.89    71.8 1103.57
   131.9 1075.84     147 1067.14   157.1  1057.1   160.3 1056.21   197.3 1055.75
   227.5 1052.14   300.2 1049.95   384.4 1049.62   389.8 1047.86   394.7 1046.67
   407.8 1047.91   412.5 1050.43   417.2 1051.31   429.7 1049.51   540.5 1048.54
   557.8 1051.64   578.5    1051   600.3 1053.85   605.5 1056.26   615.4 1065.86
   621.1  1070.2   636.3  1079.8   666.6 1095.02   717.8  1118.2   730.7 1122.78
#Mann= 7 ,-1,0
       0      .1       0      50     .06       0   389.8    .045       0
   407.8     .06       0  489.01      .1       0  519.01     .06       0
  570.55      .1       0
Bank Sta=389.8,407.8
XS Rating Curve= 0 ,0
Exp/Cntr(USF)=0,0
Exp/Cntr=0.3,0.1

Type RM Length L Ch R = 1 ,5000    ,501.5,500,496.2
BEGIN DESCRIPTION:
Structure XS 1
END DESCRIPTION:
XS GIS Cut Line= 6
1697383.18515384 438639.624987171697264.43276668438776.553519085
 1697149.7748595438908.7599475831697098.19130126438963.299864754
1697015.62814617439009.2220170051696920.27466235439061.585101262
#Sta/Elev= 30
       0 1191.97    31.2 1181.13      70 1163.07    85.1 1156.81    96.3 1151.02
   121.9 1135.71   130.4 1131.67   147.4 1125.92   163.4  1122.9   186.5 1115.12
   228.9 1093.05   246.7 1082.05   260.9 1076.65   267.2 1072.16   297.7 1045.19
     303 1044.49   320.4 1045.17   328.9 1047.38     422 1048.06   436.7 1051.59
   461.2 1051.39   474.9 1054.71   479.5  1057.8   488.6 1066.42   495.5 1071.96
   510.2 1079.63   538.9 1092.81     580 1108.62   607.4 1120.38   634.6 1128.11
#Mann= 5 ,-1,0
       0      .1       0   297.7    .045       0   320.4      .1       0
  336.25     .06       0  491.32      .1       0
Bank Sta=297.7,320.4
XS Rating Curve= 0 ,0
Exp/Cntr(USF)=0,0
Exp/Cntr=0.3,0.1

Type RM Length L Ch R = 1 ,4500    ,452.5,452.5,449.7
XS GIS Cut Line= 6
1696892.44925867438377.1077956711696845.07533768438458.211308002
1696803.77325493438535.3499332521696721.16843326 438689.62718375
 1696685.7662731 438755.745817931696600.21132609438915.532899916
#Sta/Elev= 30
       0 1178.33    13.2 1173.56      32    1163    43.7 1159.48    54.9 1153.89
    84.6 1135.06   105.6 1126.68   123.8 1122.39   141.9 1114.23   163.8 1102.74
   191.8 1084.78   219.1 1073.53   258.9 1048.27   296.2 1039.97   300.7 1039.03
  315.371039.952     328 1042.81   388.9 1042.04   405.1 1047.81   427.8 1048.23
   432.3 1050.59   445.9 1065.53   450.5 1068.97   483.5 1089.38   518.5 1113.91
   541.2 1124.68     579 1135.54   586.9 1140.23   595.9 1149.25   612.7 1160.36
#Mann= 5 ,-1,0
       0      .1       0   296.2    .045       0  315.37      .1       0
  366.43     .06       0  481.43      .1       0
Bank Sta=296.2,315.37
XS Rating Curve= 0 ,0
Exp/Cntr(USF)=0,0
Exp/Cntr=0.3,0.1

Type RM Length L Ch R = 1 ,4048    ,132.4,124.7,114.8
BEGIN DESCRIPTION:
Structure XS 4
END DESCRIPTION:
XS GIS Cut Line= 3
1696527.10438654 438214.379039061696393.23904438438338.901841053
1696260.29729407438684.807175402
#Sta/Elev= 30
       0  1130.4     3.2 1129.89    14.9 1125.67    36.9 1116.88    82.9 1093.76
   114.8 1080.52   132.4 1076.45     150  1071.1   179.4 1066.34   194.3 1061.76
   223.1 1048.88   231.7  1044.2   241.7 1037.64   246.9 1035.41   257.4 1034.09
   267.2 1035.44   270.3 1036.83   274.6 1037.55   308.8 1036.59   376.9  1036.6
   392.4 1039.72   411.7 1040.13   424.6 1046.19   433.1 1053.62     446 1063.12
   463.1 1077.29   488.8 1093.85   503.8 1101.66   527.4 1110.83   553.4 1118.52
#Mann= 5 ,-1,0
       0      .1       0   246.9    .045       0   267.2      .1       0
  352.83     .06       0  462.83      .1       0
Bank Sta=246.9,267.2
XS Rating Curve= 0 ,0
Exp/Cntr(USF)=0,0
Exp/Cntr=0.3,0.1

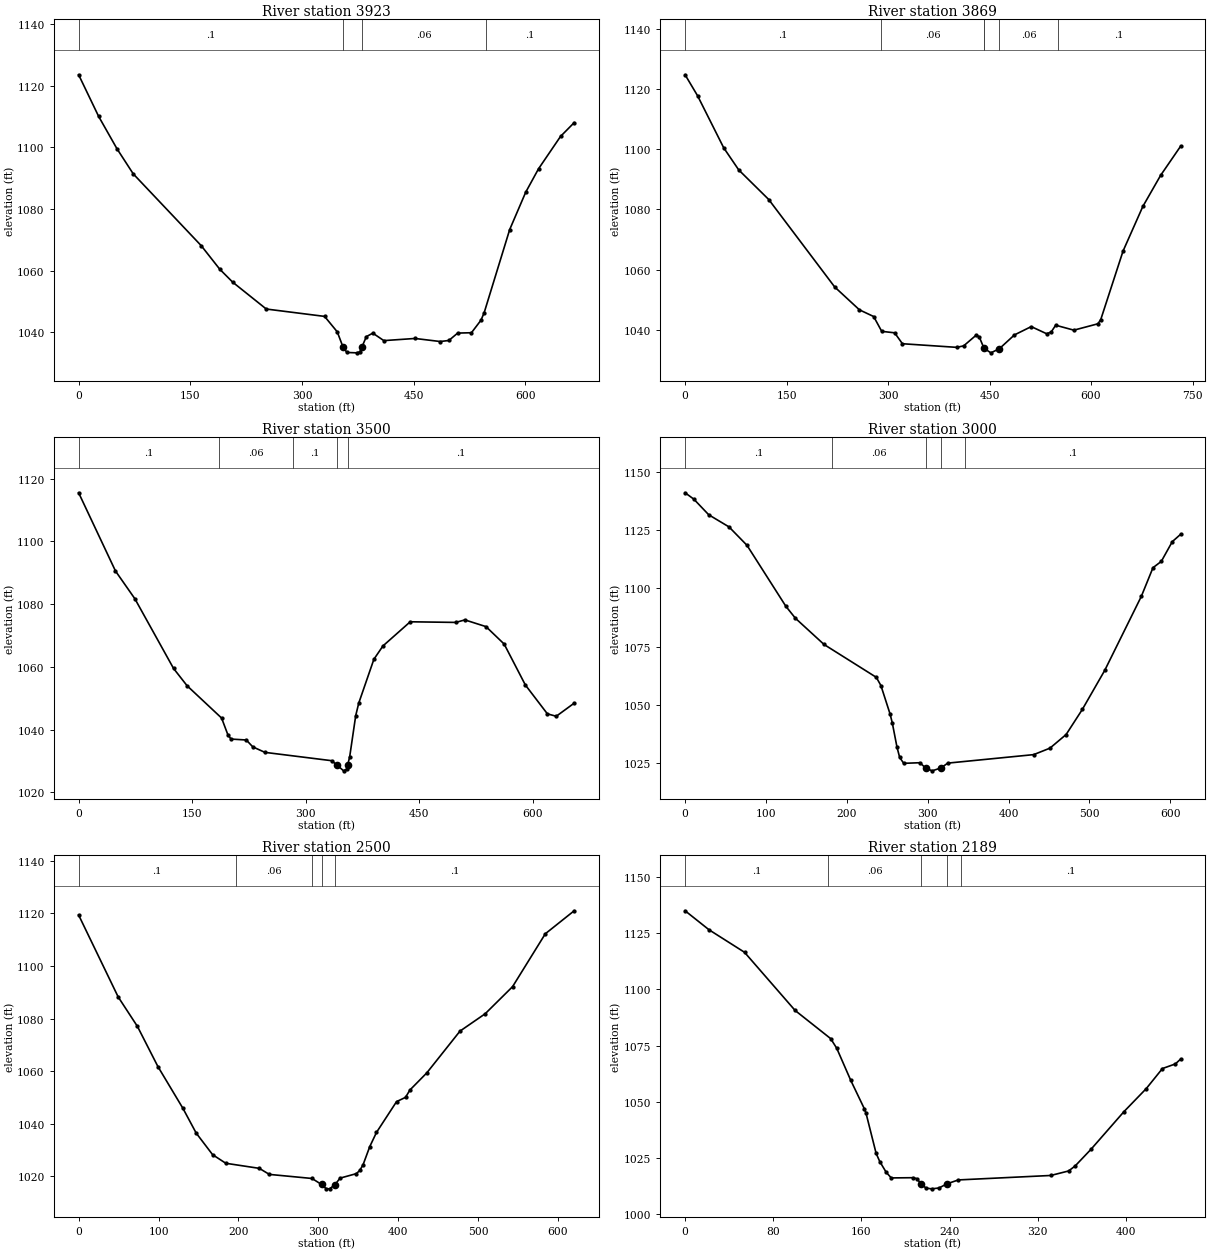
Type RM Length L Ch R = 1 ,3923    ,54.3,54.2,55.1
BEGIN DESCRIPTION:
Structure XS 3
END DESCRIPTION:
XS GIS Cut Line= 6
1696455.85542857 438171.158526281696219.22682111438318.667268593
1696259.17710548438434.4206566581696281.71316334438483.590237428
1696307.32231999438516.3699579421696245.86034403 438673.09799665
#Sta/Elev= 30
       0 1123.61    26.9 1110.08    51.5 1099.58    73.4 1091.41   164.7 1068.09
   189.5 1060.47     207 1056.23   252.1 1047.51   330.4 1045.12   347.4 1040.11
   355.2 1035.15   360.4  1033.4   373.4 1033.28   377.8 1033.58  380.781035.289
   386.5 1038.54   395.2 1039.68     410 1037.25   451.9 1037.95   485.6 1036.96
   497.3 1037.29   509.2  1039.7   527.7 1039.81   540.5 1043.88   544.8 1046.33
   579.1 1073.34   600.6 1085.46   617.8 1093.06   647.4 1103.59   665.7 1108.06
#Mann= 4 ,-1,0
       0      .1       0   355.2    .045       0  380.78     .06       0
  547.31      .1       0
Bank Sta=355.2,380.78
XS Rating Curve= 0 ,0
Exp/Cntr(USF)=0,0
Exp/Cntr=0.3,0.1

Type RM Length L Ch R = 1 ,3869    ,340.8,368.6,381.5
BEGIN DESCRIPTION:
Structure XS 2
END DESCRIPTION:
XS GIS Cut Line= 6
1696447.66049844438148.6224684271696157.76484514438286.911914345
1696172.10597287438365.7881168321696203.86132712 438441.59122052
1696267.37203561438538.906015796 1696234.5923151438666.951799053
#Sta/Elev= 30
       0 1124.67    18.4 1117.73    57.1 1100.44    79.3 1093.11   123.6 1083.31
   221.1  1054.3   257.6 1046.73   278.7  1044.5   290.6 1039.59   309.7  1039.1
   321.2 1035.48   401.4 1034.28   411.7 1034.77   430.4 1038.36   434.7 1037.76
  441.841033.949     452 1032.46   464.6 1033.85   486.8 1038.41   511.6 1041.16
   534.3  1038.8     541 1039.34   547.7 1041.62   574.6 1039.98   610.1 1042.09
   614.3 1043.47   647.3 1066.22   676.5 1080.99   702.8 1091.31   732.4 1100.99
#Mann= 6 ,-1,0
       0      .1       0     290     .06       0  441.36      .1       0
  441.84    .045       0   464.6     .06       0  551.11      .1       0
Bank Sta=441.84,464.6
XS Rating Curve= 0 ,0
Exp/Cntr(USF)=0,0
Exp/Cntr=0.3,0.1

Type RM Length L Ch R = 1 ,3500    ,505.2,500,492.8
BEGIN DESCRIPTION:
Structure XS 1
END DESCRIPTION:
XS GIS Cut Line= 6
1696359.96771209438068.0618258421696245.40068401438118.997419506
1696150.71058467438144.5574077521695975.77655134438139.743441001
1695900.80524459438137.6801249241695719.62384842438132.692274004
#Sta/Elev= 30
       0 1115.47    48.7 1090.53    74.3 1081.69   125.4 1059.48   143.3 1053.96
   188.9 1043.66   197.1 1038.39   201.3 1036.97   221.5 1036.67   230.1 1034.48
   246.1 1032.73   334.1 1030.08   341.3  1028.7   350.1 1026.84   354.1 1027.38
  355.561028.811   358.1  1031.3   366.1 1044.47   370.1 1048.44   390.1 1062.41
   402.1 1066.66   438.1 1074.35   498.2 1074.15   510.3 1074.95   538.2 1072.81
   562.2 1067.25   590.2 1054.21   619.3 1045.01     631 1044.23   654.7 1048.41
#Mann= 5 ,-1,0
       0      .1       0  185.38     .06       0  283.46      .1       0
   341.3    .045       0  355.56      .1       0
Bank Sta=341.3,355.56
XS Rating Curve= 0 ,0
Exp/Cntr(USF)=0,0
Exp/Cntr=0.3,0.1

Type RM Length L Ch R = 1 ,3000    ,492.1,500.1,508.4
XS GIS Cut Line= 6
1696211.35810117437504.601666674 1696007.3047035437659.605621755
1695927.67362918437720.0943459271695867.95065151437765.461381167
1695798.01411159437818.0478901711695719.51197201 437869.69017534
#Sta/Elev= 30
       0 1141.14    10.8  1138.4    29.2 1131.69    54.3 1126.47    76.5 1118.57
   124.6 1092.34   136.4  1087.2   171.8 1075.93   236.4 1061.81   242.1 1058.29
   253.5 1045.97   256.2 1042.19     262 1031.77   265.3 1027.38   270.3 1024.84
   290.4  1025.1   297.5 1022.76   305.5 1021.61   316.3 1022.86   324.8 1024.93
     431 1028.58   451.1 1031.36   471.1 1037.22   491.1 1047.98   518.8 1064.76
   564.1 1096.61   578.5 1108.93   588.8 1111.65   602.4 1120.14   612.7 1123.29
#Mann= 5 ,-1,0
       0      .1       0  181.25     .06       0   297.5    .045       0
   316.3     .06       0  346.25      .1       0
Bank Sta=297.5,316.3
XS Rating Curve= 0 ,0
Exp/Cntr(USF)=0,0
Exp/Cntr=0.3,0.1

Type RM Length L Ch R = 1 ,2500    ,318.4,311.4,302.7
XS GIS Cut Line= 6
1696081.51945008437317.7824864981695982.57542226437324.445530921
1695897.52900442437302.8888155071695658.94319551437228.209830999
1695574.76226151437204.2699182631695479.24407984437196.859500006
#Sta/Elev= 30
       0 1119.35    49.5 1088.21    73.6    1077    99.2 1061.75   130.6 1045.82
   147.1 1036.46   167.7 1028.23   184.2 1024.97   226.1 1023.04   238.7 1020.74
   292.1 1019.19  303.971016.916   309.9 1015.29   314.1 1015.25   320.8 1016.84
   327.2 1019.32   347.6 1021.03   351.8 1022.23     356 1024.41   364.4 1031.33
   372.8 1036.71   397.9 1048.41   409.1 1050.03   414.7 1052.85   435.7 1059.32
   477.3 1075.22   508.8 1081.81   543.1 1092.12   584.1 1112.23   620.2 1120.97
#Mann= 5 ,-1,0
       0      .1       0   196.9     .06       0  291.91      .1       0
  303.97    .045       0   320.8      .1       0
Bank Sta=303.97,320.8
XS Rating Curve= 0 ,0
Exp/Cntr(USF)=0,0
Exp/Cntr=0.3,0.1

Type RM Length L Ch R = 1 ,2189    ,155.8,155,153.8
BEGIN DESCRIPTION:
Structure XS 4
END DESCRIPTION:
XS GIS Cut Line= 2
1695915.13454529 436861.954211311695523.31444852 437082.29539514
#Sta/Elev= 30
       0 1134.93    21.7 1126.49    53.9 1116.49    99.8 1090.64     132 1078.15
   137.5  1073.9   150.3 1059.55   162.7 1046.86   164.1 1045.02   173.3 1027.11
   176.6  1023.5   182.4 1018.75     187 1016.24   206.8 1016.34     210 1015.94
  214.051013.696   218.5 1011.71   223.7 1011.39   230.3 1011.77   237.5 1013.62
   247.9 1015.35   331.7 1017.33   347.8 1019.32   353.7  1021.5   368.2 1028.96
   398.1  1045.7   418.3 1055.92     433 1064.84   444.7 1066.88   449.5 1069.04
#Mann= 5 ,-1,0
       0      .1       0     130     .06       0  214.05    .045       0
   237.5     .06       0     250      .1       0
Bank Sta=214.05,237.5
XS Rating Curve= 0 ,0
Exp/Cntr(USF)=0,0
Exp/Cntr=0.3,0.1