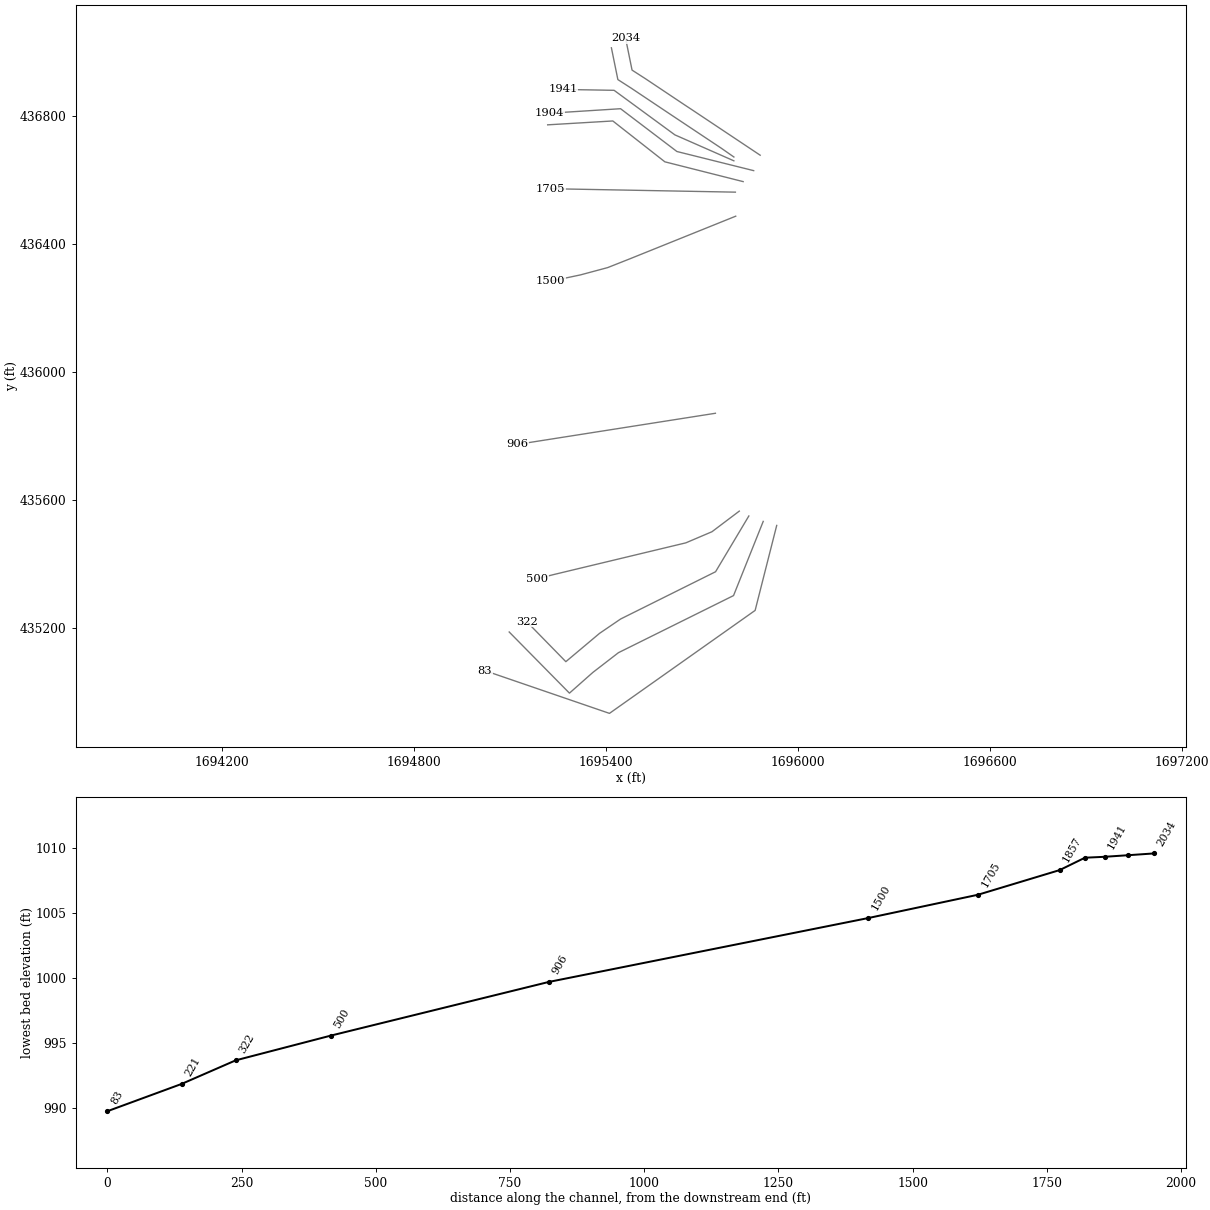
HEC-RAS study RCKCMPRN1.prj: RCKCMPRN1

--- RCKCMPRN1.g01 (geometry) --- (continued)

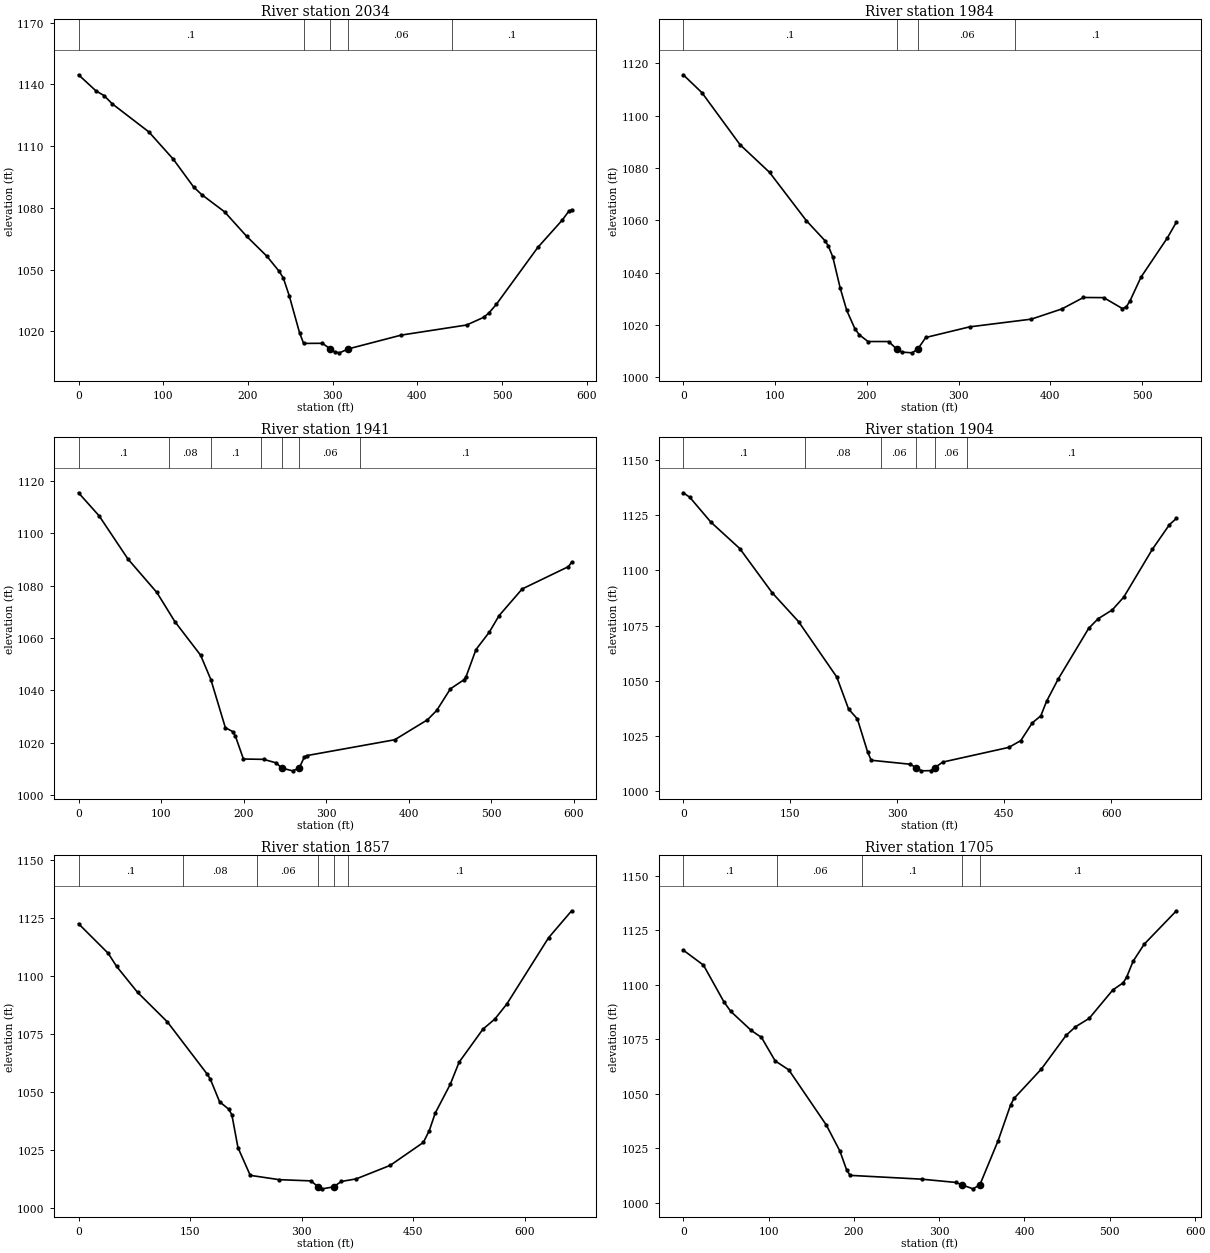
Type RM Length L Ch R = 1 ,2034    ,49.2,49.3,49.3
BEGIN DESCRIPTION:
Structure XS 3
END DESCRIPTION:
XS GIS Cut Line= 6
1695881.21605363436678.5244253091695668.00289738  436820.6658733
 1695644.2363278436836.3252741461695522.39393663436917.738185714
1695480.80289077436944.4618718641695460.62186299437043.762553651
#Sta/Elev= 30
       0 1144.71    20.6 1136.89    30.2 1134.58    39.7 1130.63      83 1116.95
   111.9 1103.65   135.9 1090.14   145.5 1086.43   172.4 1078.09   198.4 1066.21
   222.5 1056.44   236.9 1049.11   241.7 1045.96   248.8 1037.18   260.9 1019.26
   265.7 1014.13   287.8 1014.19  297.281011.429   302.3 1009.98     308 1009.55
   318.6 1011.49   381.1 1018.19   458.1 1023.08   478.3 1026.84   484.7 1029.08
     493 1033.05     542 1060.76   570.6 1073.92   578.7 1078.42     582 1079.11
#Mann= 5 ,-1,0
       0      .1       0  266.25     .06       0  297.28    .045       0
   318.6     .06       0  441.25      .1       0
Bank Sta=297.28,318.6
XS Rating Curve= 0 ,0
Exp/Cntr(USF)=0,0
Exp/Cntr=0.3,0.1

Type RM Length L Ch R = 1 ,1984    ,43.9,43.3,42.8
BEGIN DESCRIPTION:
Structure XS 2
END DESCRIPTION:
XS GIS Cut Line= 6
1695799.06854824436672.881639662 1695758.8628982 436700.91464586
1695599.88793762436806.7123178741695478.04554646436888.125229442
 1695436.4545006436914.8489155921695416.27347282437014.149597379
#Sta/Elev= 30
       0 1115.55    20.4 1108.69    61.9 1088.85      94  1078.3     134 1059.91
   154.6 1052.14   158.1 1050.17   162.9 1046.02   170.9 1034.25   178.1 1025.63
   186.9 1018.67   191.7 1016.32   201.3 1013.73   223.8 1013.72   232.5 1010.87
   238.2  1009.7   249.3 1009.41   255.5 1010.83   264.2 1015.27   311.9 1019.32
   379.2 1022.27   412.6 1026.18     436 1030.54   458.1 1030.48   478.5 1026.31
   482.6 1026.91   486.7 1029.21   498.7 1038.29   527.5 1053.32   537.3 1059.31
#Mann= 4 ,-1,0
       0      .1       0   232.5    .045       0   255.5     .06       0
  361.51      .1       0
Bank Sta=232.5,255.5
XS Rating Curve= 0 ,0
Exp/Cntr(USF)=0,0
Exp/Cntr=0.3,0.1

Type RM Length L Ch R = 1 ,1941    ,36.8,36.6,36.5
BEGIN DESCRIPTION:
Structure XS 4 AND 1
END DESCRIPTION:
XS GIS Cut Line= 4
1695798.97141071436660.9735499091695614.58548282436742.103358181
 1695424.6679771436881.3147337391695264.25221983436884.080522657
#Sta/Elev= 30
       0 1115.39      25 1106.58    59.9 1090.11    94.9 1077.36   116.7 1066.24
   147.9 1053.42   160.4 1044.06   177.9 1025.76   186.7 1024.28     190 1022.58
   199.8  1013.8   224.3 1013.67   239.3 1012.34   246.2 1010.36   259.3 1009.29
  267.371010.374   273.6 1014.58   276.5  1015.1   383.1 1021.15   422.7 1028.76
   433.9 1032.32   450.5 1040.58   466.8 1044.01   469.5 1045.21   481.5 1055.56
   497.5 1062.15   509.5 1068.52   537.5  1078.7   593.5 1087.21   597.4  1088.9
#Mann= 7 ,-1,0
       0      .1       0     110     .08       0     160      .1       0
  221.45     .06       0   246.2    .045       0  267.37     .06       0
  341.45      .1       0
Bank Sta=246.2,267.37
XS Rating Curve= 0 ,0
Exp/Cntr(USF)=0,0
Exp/Cntr=0.3,0.1

Type RM Length L Ch R = 1 ,1904    ,47.3,47.2,47.2
BEGIN DESCRIPTION:
Structure XS 3
END DESCRIPTION:
XS GIS Cut Line= 4
1695860.91708219 436630.263489731695620.98212773436690.079206668
1695444.89541045436823.8244613931695222.43471038436809.710640542
#Sta/Elev= 30
       0 1135.21     9.1 1133.18    38.8 1121.88    79.2 1109.94   124.5 1089.97
   161.6 1076.84   215.2 1051.72   231.7 1037.25   244.1 1032.71   258.4  1017.8
   263.4 1014.02   317.5 1012.23  326.831010.663   333.8 1009.22   346.7 1009.32
   352.4 1010.62   363.8 1013.19   456.4 1019.85   473.2 1022.93   489.2 1030.94
   501.2 1034.12   509.3 1040.74   525.6 1050.81   568.4 1073.82   581.5 1078.12
   601.4 1082.13   617.5 1087.94   657.6 1109.61   681.6 1120.79   691.3  1123.6
#Mann= 6 ,-1,0
       0      .1       0     170     .08       0  277.28     .06       0
  326.83    .045       0   352.4     .06       0  397.28      .1       0
Bank Sta=326.83,352.4
XS Rating Curve= 0 ,0
Exp/Cntr(USF)=0,0
Exp/Cntr=0.3,0.1

Type RM Length L Ch R = 1 ,1857    ,145.6,152.2,158.9
BEGIN DESCRIPTION:
Structure XS 2
END DESCRIPTION:
XS GIS Cut Line= 4
1695827.98483354436595.9870676651695583.34527213436657.819044724
1695420.70028899436785.5155190851695217.05801673436773.417958356
#Sta/Elev= 30
       0 1122.58    39.9 1109.83    51.2 1104.19    79.4 1092.99   119.5 1080.25
   173.1  1057.7   177.3 1055.53   189.7 1045.81     202 1042.61   206.2 1040.21
   214.4 1026.06   230.9 1014.09   269.7 1012.23   312.4  1011.7   322.6 1009.07
     328 1008.27   342.9 1009.12   353.4 1011.45   373.4 1012.56   419.2  1018.4
   463.7 1028.28   471.7 1033.41   479.7 1040.95   499.8 1053.29   511.8 1062.89
   543.8 1077.11   559.9  1081.5   575.9 1087.95     632  1116.5   663.1 1128.16
#Mann= 6 ,-1,0
       0      .1       0     140     .08       0     240     .06       0
   322.6    .045       0   342.9     .06       0  362.33      .1       0
Bank Sta=322.6,342.9
XS Rating Curve= 0 ,0
Exp/Cntr(USF)=0,0
Exp/Cntr=0.3,0.1

Type RM Length L Ch R = 1 ,1705    ,200.7,204.9,208.8
BEGIN DESCRIPTION:
Structure XS 1
END DESCRIPTION:
XS GIS Cut Line= 2
1695803.78971208436563.0548190141695225.79514392436573.808206328
#Sta/Elev= 30
       0 1115.88    23.7    1109    47.7 1092.13    55.7 1087.78    79.7 1079.03
    91.7 1075.84   107.7 1065.08   123.7 1060.96   167.7 1035.65   183.7 1023.63
   191.7 1014.84   195.7 1012.56   279.7 1010.81   319.7 1009.31   327.1 1008.15
   339.7 1006.38   347.7 1008.23   369.1 1028.47   383.7 1044.86   387.7 1047.83
   419.7  1061.3   448.9 1076.84   459.8 1080.72   475.8 1084.56   503.6 1097.63
   515.8 1100.92   519.8 1103.54   527.4 1110.82   540.3 1118.59   578.1 1133.94
#Mann= 5 ,-1,0
       0      .1       0     110     .06       0     210      .1       0
   327.1    .045       0   347.7      .1       0
Bank Sta=327.1,347.7
XS Rating Curve= 0 ,0
Exp/Cntr(USF)=0,0
Exp/Cntr=0.3,0.1

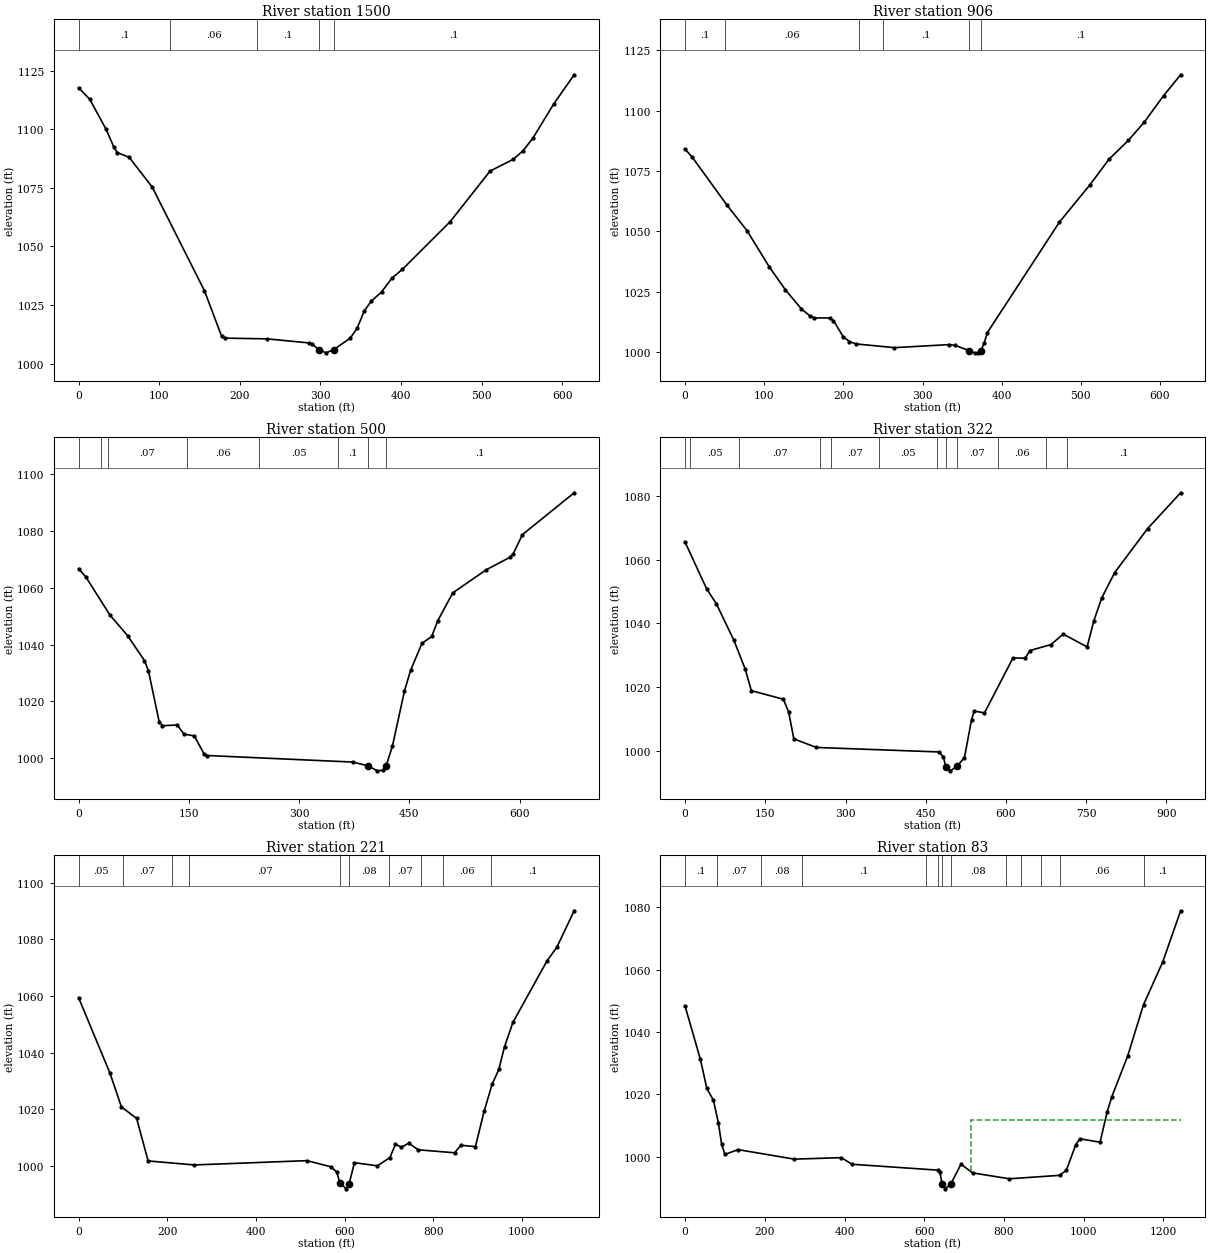
Type RM Length L Ch R = 1 ,1500    ,596.4,594.3,589.9
XS GIS Cut Line= 6
1695804.78411117436487.9229257551695567.08970468436392.186568677
1695474.33037576436354.8270633371695404.57887484436327.259861261
1695319.53770635 436304.436416091695226.13369368436284.726481751
#Sta/Elev= 30
       0 1117.66    13.7 1112.84    33.9 1100.08    43.8  1092.3    48.2    1090
    62.6 1088.05    91.3 1075.32     156 1031.16   177.5 1011.58   181.8 1010.86
   233.7 1010.56   285.3 1008.84   289.6 1008.43  297.65 1006.01   306.9 1004.59
   316.7 1005.98   337.1 1010.92   345.7 1015.19   354.3 1022.46   362.9 1026.57
   375.8 1030.56   388.7 1036.45   401.6 1040.19   460.7 1060.45   510.4 1082.14
   539.2 1087.15   551.4 1090.83   563.7 1096.26   589.6 1110.87   614.8 1123.23
#Mann= 5 ,-1,0
       0      .1       0  113.75     .06       0  221.25      .1       0
  297.65    .045       0   316.7      .1       0
Bank Sta=297.65,316.7
XS Rating Curve= 0 ,0
Exp/Cntr(USF)=0,0
Exp/Cntr=0.3,0.1

Type RM Length L Ch R = 1 ,906     ,404.1,405.7,406.3
XS GIS Cut Line= 2
1695741.33101332435871.9896538931695122.82943917 435774.78535073
#Sta/Elev= 30
       0  1084.1     9.3 1080.64    53.1 1060.82    78.2 1050.34   106.5 1035.24
   126.8 1025.77     147 1017.88     158 1014.91   163.2 1014.17   183.4 1014.14
   187.5 1013.07   199.6 1006.45   207.7 1004.36   215.8  1003.4   264.4 1001.85
   333.6 1003.11   341.4 1002.77     3591000.588   365.7   999.7   369.7  999.77
   373.7 1000.62   377.8 1003.64   381.8 1008.04   472.9 1053.84   511.4 1069.27
   535.7 1079.96     560 1087.69   580.3 1095.34   604.5 1106.23   626.1  1114.9
#Mann= 6 ,-1,0
       0      .1       0      50     .06       0     220     .07       0
     250      .1       0     359    .045       0   373.7      .1       0
Bank Sta=359,373.7
XS Rating Curve= 0 ,0
Exp/Cntr(USF)=0,0
Exp/Cntr=0.3,0.1

Type RM Length L Ch R = 1 ,500     ,175.9,177.6,179.7
BEGIN DESCRIPTION:
Structure XS 4
END DESCRIPTION:
XS GIS Cut Line= 6
1695815.94701593435566.1979179341695730.55557904435501.776803127
1695648.90647018435467.0355318341695563.82265083435446.615297094
1695235.64154868435367.8529874241695183.73573268435354.778451073
#Sta/Elev= 30
       0 1066.63     9.8 1063.78    42.6 1050.35    66.8 1043.06    89.6 1034.33
      95 1030.74   109.6 1012.82     114 1011.45   134.2 1011.72   143.3  1008.5
   157.4 1007.88   170.5 1001.61   174.8 1000.98   373.4  998.67     394  997.32
   406.3  995.59   414.5  995.82  418.24 997.264   426.9 1004.24   443.3 1023.64
   451.6  1030.9   467.1 1040.41   480.4 1042.84   488.6 1048.37   509.1 1058.17
   554.4 1066.25   587.3 1070.73   591.4 1071.98   603.8 1078.64   674.2 1093.35
#Mann= 8 ,-1,0
       0      .1       0      30     .05       0      40     .07       0
  146.97     .06       0   245.7     .05       0   353.2      .1       0
     394    .045       0  418.24      .1       0
Bank Sta=394,418.24
XS Rating Curve= 0 ,0
Exp/Cntr(USF)=0,0
Exp/Cntr=0.3,0.1

Type RM Length L Ch R = 1 ,322     ,99.2,100.9,99.9
BEGIN DESCRIPTION:
Structure XS 3
END DESCRIPTION:
XS GIS Cut Line= 6
1695845.77921939435550.9576252291695741.79690981435376.716998354
1695445.30681085435229.174532049 1695379.2639926435184.209208985
1695273.87651667435095.6837292021695151.62704459435220.743533975
#Sta/Elev= 30
       0 1065.55    40.1 1050.95    58.4 1046.21    91.3  1034.7   112.5 1025.61
   123.9  1018.9   183.8 1016.18   193.8 1012.06   203.3 1003.74   245.4 1001.04
   474.2  999.63   482.9  998.09   487.3  995.02   496.1  993.69   508.3  995.11
   522.4  997.86   535.6 1009.75   540.5 1012.48   559.8  1011.9   613.1 1029.15
     636 1029.11   644.7  1031.5   684.2 1033.37     707 1036.68   751.7 1032.64
   764.1 1040.74     779 1048.01   803.3 1056.01   864.8 1069.82   926.6 1081.08
#Mann= 12 ,-1,0
       0      .1       0      10     .05       0     100     .07       0
  252.91     .05       0  272.91     .07       0  362.91     .05       0
  471.05      .1       0   487.3    .045       0   508.3     .07       0
  584.21     .06       0   674.1     .07       0   714.1      .1       0
Bank Sta=487.3,508.3
XS Rating Curve= 0 ,0
Exp/Cntr(USF)=0,0
Exp/Cntr=0.3,0.1

Type RM Length L Ch R = 1 ,221     ,136.5,138.2,139.3
BEGIN DESCRIPTION:
Structure XS 2
END DESCRIPTION:
XS GIS Cut Line= 6
1695890.74454246435534.0956290791695798.00356364435302.243182029
1695438.28097912435123.7870561171695358.18649742435061.959736904
1695285.11784744434997.322084999 1695096.8255571435188.424708022
#Sta/Elev= 30
       0 1059.38    70.6 1032.79    96.5 1020.83   130.9 1016.76   156.8 1001.74
   260.7 1000.32   515.2 1001.84   568.7  999.69   582.1  997.93  589.86 993.864
   604.1  991.88   610.6  993.75   622.4 1001.12   674.2 1000.01   702.4 1002.92
     715 1007.64   728.6 1006.59     745 1008.02   766.3 1005.67   848.4 1004.62
   862.8 1007.29   895.4 1006.77   915.2 1019.38   933.1  1028.8   948.3 1034.08
   961.2 1042.16   980.3 1050.74  1056.6 1072.31  1079.3 1077.27  1118.3 1090.11
#Mann= 10 ,-1,0
       0     .05       0     100     .07       0     210     .08       0
  249.71     .07       0  589.86    .045       0   610.6     .08       0
  701.27     .07       0  772.45     .08       0  822.45     .06       0
  930.01      .1       0
Bank Sta=589.86,610.6
XS Rating Curve= 0 ,0
Exp/Cntr(USF)=0,0
Exp/Cntr=0.3,0.1

Type RM Length L Ch R = 1 ,83      ,,,
BEGIN DESCRIPTION:
Structure XS 1
END DESCRIPTION:
XS GIS Cut Line= 4
1695932.89953283435521.4491319681695865.45154824435255.872692619
1695410.17765221 434934.089599441695020.94657443435067.580402287
#Sta/Elev= 30
       0 1048.25    38.1 1031.37    54.6 1021.92    71.1 1018.12    83.5  1010.9
    91.7 1004.05     100 1000.82   132.9 1002.34     274   999.3   392.2  999.77
   418.4  997.66   633.2  995.78     639  995.04   644.7  991.43   652.8  989.79
   666.6  991.39     692  997.66   721.4  994.89   813.4  993.01   939.4  994.11
   956.3  995.71   979.9 1003.92   990.2 1005.82  1040.9 1004.71  1058.6  1014.4
  1070.5 1019.28  1110.3 1032.38  1149.9 1048.75  1197.8 1062.33    1243  1078.8
#Mann= 13 ,-1,0
       0      .1       0      80     .07       0     190     .08       0
  294.01      .1       0  604.01     .07       0  634.01     .08       0
   644.7    .045       0   666.6     .08       0  804.01      .1       0
  841.52     .07       0  891.52     .08       0  941.52     .06       0
 1151.52      .1       0
#XS Ineff= 2 , 0
                          716.61         1011.72
Permanent Ineff=
       F       F
Bank Sta=644.7,666.6
XS Rating Curve= 0 ,0
Exp/Cntr(USF)=0,0
Exp/Cntr=0.3,0.1
LCMann Table=0

Chan Stop Cuts=-1
Use User Specified Reach Order=0
Composite Channel Slope=5